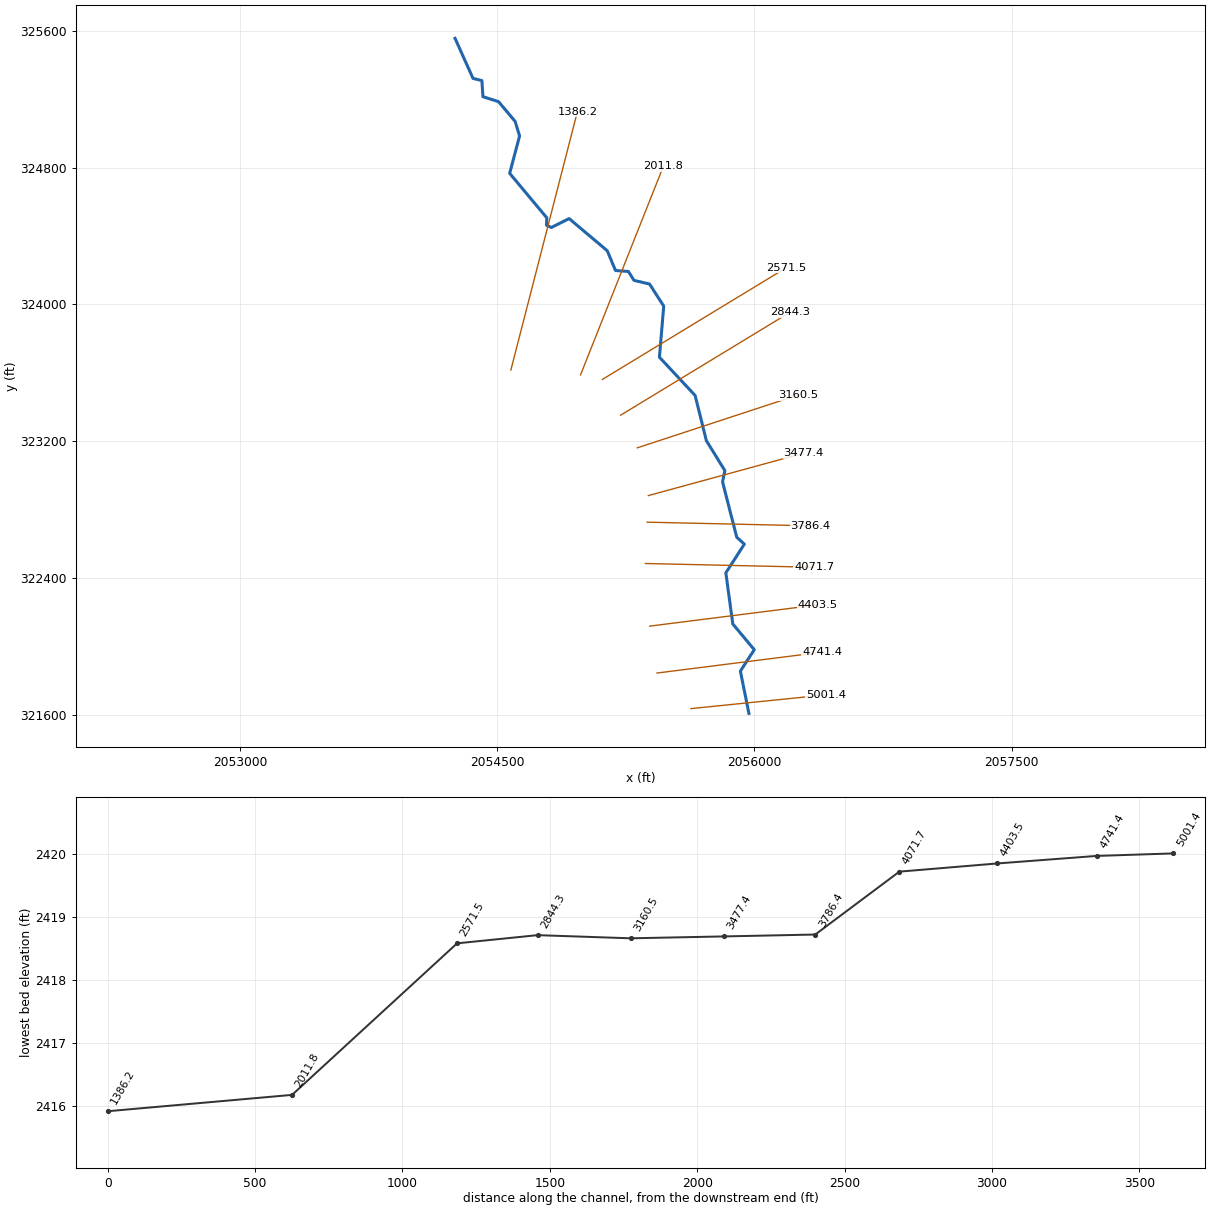
--- CallahanBr.prj (project) ---

Proj Title=CallahanBr
Current Plan=p01
Default Exp/Contr=0,0
English Units
Geom File=g01
Flow File=f01
Plan File=p01
BEGIN DESCRIPTION:
END DESCRIPTION:
DSS Export Rating Curves= 0
DSS Export Rating Curve Sorted= 0
DSS Export Volume Flow Curves= 0
DXF OffsetX= 0
DXF OffsetY= 0
DXF ScaleX= 0
DXF ScaleY= 0

--- CallahanBr.p01 (plan) ---

Plan Title=Floodplain
Program Version=4.00
Geom File=g01
Flow File=f01
K Sum by GR=0
Std Step Tol=0.01
Critical Tol=0.01
Num of Std Step Trials=20
Max Error Tol=0.3
Flow Tol Ratio=0.001
Split Flow NTrial=30
Split Flow Tol=0.02
Split Flow Ratio=0.02
Log Output Level=0
Friction Slope Method=1
Unsteady Friction Slope Method=2
Unsteady Bridges Friction Slope Method=1
Global Log Level=0
CheckData=False
Run HTab=0
Run UNet=0
Run PostProcess=0
UNET Theta=0
UNET Theta Warmup=0
UNET ZTol=0
UNET ZSATol=0
UNET MxIter=0
UNET MaxInSteps=0
UNET DtIC=0
UNET DtMin=0
UNET MaxCRTS=0
UNET WFStab=0
UNET SFStab=0
UNET WFX=0
UNET SFX=0
UNET DSS MLevel=0
UNET DZMax Abort=0
UNET Convert EG Bridges=0
UNET Use Existing IB Tables=0
UNET Froude Limit=0
UNET Froude Power=0
Write IC File=0
Echo Input=False
Echo Output=False
Write Detailed=0

--- CallahanBr.f01 (steady flow) ---

Flow Title=NFF Regression Equation
Program Version=4.00
Number of Profiles=1
Profile Names=P100yr
River Rch & RM=CallahanBr,Main      ,5001.4
523.3031
River Rch & RM=CallahanBr,Main      ,4071.7
537.6899
River Rch & RM=CallahanBr,Main      ,2844.3
586.3125
Boundary for River Rch & Prof#=CallahanBr,Main      ,1
Up Type=0
Dn Type=3
Dn Slope=0.001804

--- CallahanBr.g01 (geometry) ---

Geom Title=USGS 10m DEM
Program Version=4.00

River Reach=CallahanBr     ,Main
Reach XY= 30
     2055967.419      321609.037     2055917.751      321856.141
     2055998.731      321981.468     2055873.405      322131.860
     2055832.914      322430.716     2055940.888      322598.462
     2055896.542      322638.952     2055813.633      322962.873
     2055827.130      323028.429     2055719.156      323203.887
     2055653.601      323468.037     2055445.365      323691.697
     2055470.431      323990.554     2055387.522      324119.737
     2055296.901      324140.946     2055264.123      324193.005
     2055188.927      324198.789     2055140.725      324314.475
     2054918.510      324502.225     2054814.393      324450.166
     2054786.331      324463.333     2054788.363      324506.563
     2054571.451      324766.857     2054629.295      324985.215
     2054603.265      325070.534     2054506.378      325186.220
     2054415.275      325215.142     2054409.491      325309.137
     2054357.432      325322.152     2054252.699      325556.260

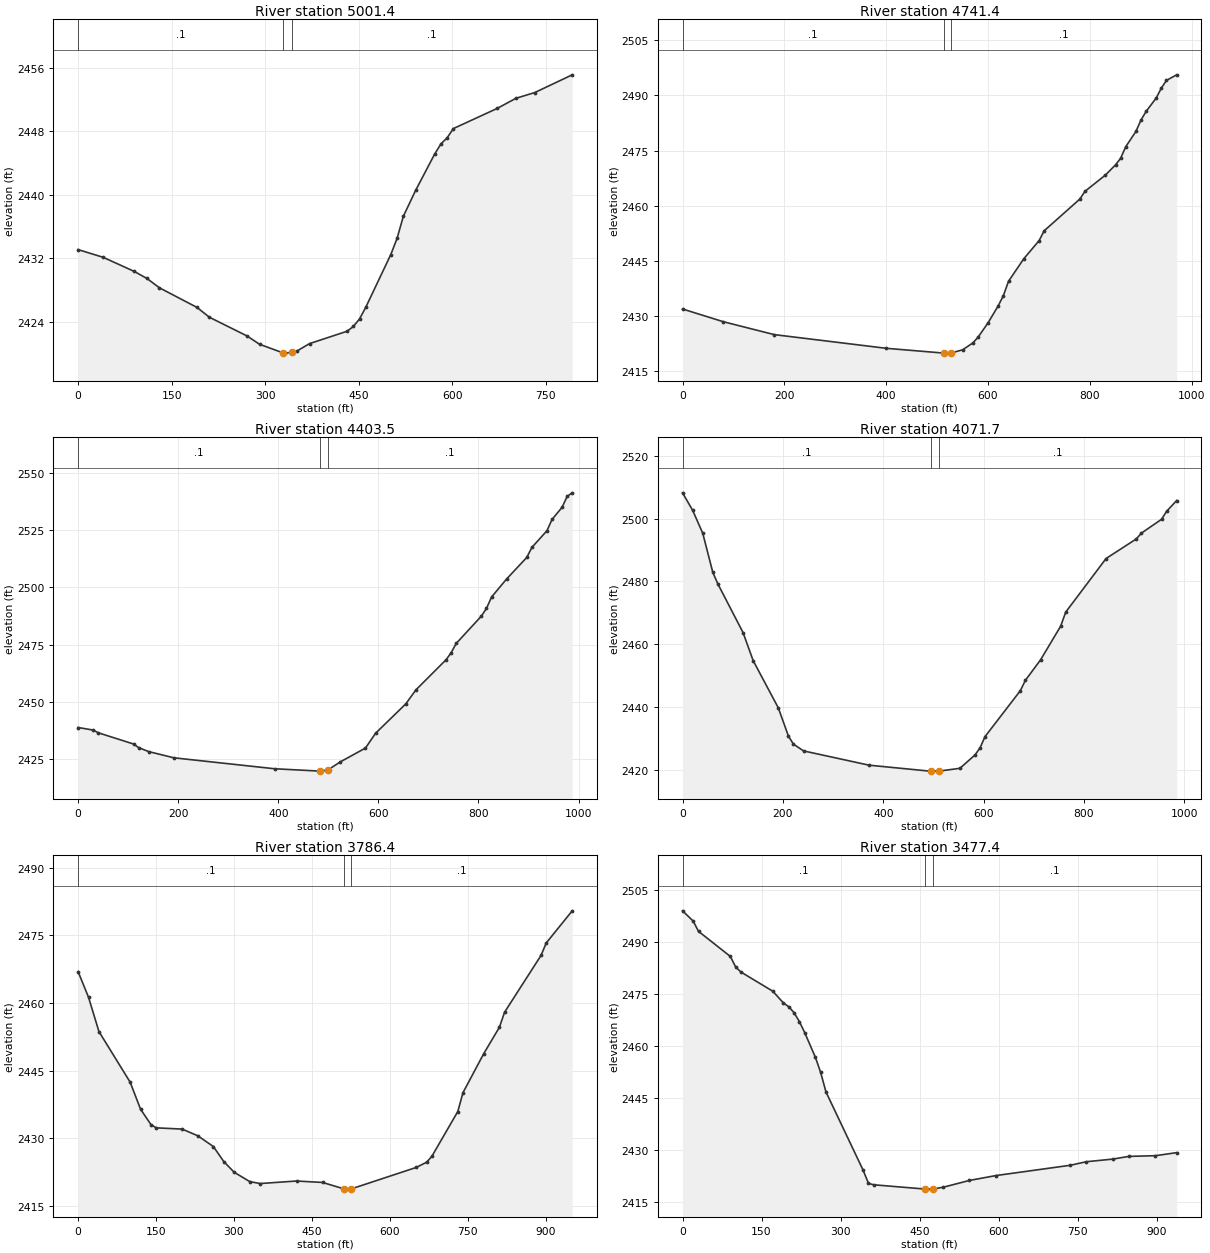
Type RM Length L Ch R = 1 ,5001.4,258.1,260,261.8
XS GIS Cut Line= 2
     2055629.559      321636.898     2056417.579      321717.260
#Sta/Elev= 30
       0 2433.07    40.1 2432.10    90.2 2430.31   110.3 2429.43   130.4 2428.25
   190.5 2425.78   210.6 2424.53   270.7 2422.18   290.8 2421.13   327.8 2420.06
   330.9 2420.01   342.8 2420.11   350.9 2420.28   371.0 2421.21   431.2 2422.77
   441.2 2423.37   451.2 2424.33   461.2 2425.80   501.3 2432.45   511.4 2434.50
   521.4 2437.28   541.4 2440.59   571.5 2445.11   581.6 2446.40   591.6 2447.18
   601.6 2448.34   671.8 2450.88   701.9 2452.16   732.0 2452.88   792.1 2455.12
#Mann= 3 , 0 , 0
       0     0.1       0   327.8   0.045       0   342.8     0.1       0
Bank Sta=   327.8,   342.8
Exp/Cntr=0.3,0.1

Type RM Length L Ch R = 1 ,4741.4,337.2,337.9,337.6
XS GIS Cut Line= 2
     2055431.400      321844.991     2056394.228      321966.943
#Sta/Elev= 30
       0 2431.96    80.0 2428.51   180.1 2425.00   400.2 2421.28     513 2419.98
   520.3 2419.97     528 2420.02   550.3 2420.88   570.3 2422.75   580.3 2424.27
   600.3 2428.24   620.3 2432.88   630.3 2435.63   640.3 2439.50   670.4 2445.64
   700.4 2450.55   710.4 2453.23   780.4 2461.84   790.4 2463.94   830.4 2468.33
   850.5 2471.13   860.5 2472.92   870.5 2476.05   890.5 2480.21   900.5 2483.31
   910.5 2485.64   930.5 2489.32   940.5 2492.00   950.5 2494.08   970.5 2495.60
#Mann= 3 , 0 , 0
       0     0.1       0     513   0.045       0     528     0.1       0
Bank Sta=     513,     528
Exp/Cntr=0.3,0.1

Type RM Length L Ch R = 1 ,4403.5,327,331.8,333.3
XS GIS Cut Line= 2
     2055388.840      322119.265     2056368.378      322243.333
#Sta/Elev= 30
       0 2438.89    30.2 2437.76    40.3 2436.58   110.8 2431.68   120.9 2430.12
   141.0 2428.38   191.4 2425.66   392.9 2420.88   483.6 2419.85     484 2419.85
     499 2420.33   523.9 2423.88   574.3 2429.92   594.4 2436.37   654.9 2449.22
   675.0 2455.30   735.5 2468.50   745.6 2471.58   755.6 2475.58   806.0 2487.53
   816.1 2490.88   826.2 2495.83   856.4 2503.74   896.7 2513.13   906.8 2517.49
   937.0 2524.79   947.1 2529.70   967.2 2534.99   977.3 2539.75   987.4 2541.31
#Mann= 3 , 0 , 0
       0     0.1       0     484   0.045       0     499     0.1       0
Bank Sta=     484,     499
Exp/Cntr=0.3,0.1

Type RM Length L Ch R = 1 ,4071.7,289.4,285.2,280.5
XS GIS Cut Line= 2
     2055363.430      322485.426     2056347.801      322463.352
#Sta/Elev= 30
       0 2508.18    20.1 2502.63    40.2 2495.36    60.3 2482.90    70.3 2479.25
   120.6 2463.75   140.7 2454.85   190.9 2439.81   211.0 2430.85   221.0 2428.29
   241.1 2426.15   371.7 2421.61   492.3 2419.72   495.6 2419.72   510.6 2419.72
   552.6 2420.61   582.7 2424.84   592.8 2427.09   602.8 2430.70   673.2 2445.30
   683.2 2448.58   713.4 2455.08   753.5 2465.79   763.6 2470.27   844.0 2487.30
   904.2 2493.52   914.3 2495.36   954.5 2499.76   964.5 2502.27   984.6 2505.73
#Mann= 3 , 0 , 0
       0     0.1       0   495.6   0.045       0   510.6     0.1       0
Bank Sta=   495.6,   510.6
Exp/Cntr=0.3,0.1

Type RM Length L Ch R = 1 ,3786.4,302.3,309,314.9
XS GIS Cut Line= 2
     2055373.936      322727.052     2056325.133      322705.722
#Sta/Elev= 30
       0 2466.97    20.0 2461.30    40.1 2453.68   100.2 2442.45   120.2 2436.46
   140.2 2433.05   150.2 2432.32   200.3 2432.04   230.4 2430.56   260.4 2428.17
   280.4 2424.85   300.4 2422.47   330.5 2420.39   350.5 2419.96   420.6 2420.52
   470.7 2420.20   511.2 2418.80   520.8 2418.72   526.2 2418.78   651.0 2423.53
   671.0 2424.68   681.0 2425.97   731.1 2435.94   741.1 2440.13   781.2 2448.81
   811.2 2454.63   821.2 2457.98   891.4 2470.58   901.4 2473.34   951.4 2480.47
#Mann= 3 , 0 , 0
       0     0.1       0   511.2   0.045       0   526.2     0.1       0
Bank Sta=   511.2,   526.2
Exp/Cntr=0.3,0.1

Type RM Length L Ch R = 1 ,3477.4,316.3,317,318.2
XS GIS Cut Line= 2
     2055380.692      322882.443     2056285.443      323130.105
#Sta/Elev= 30
       0 2499.02    20.2 2496.06    30.3 2493.10    90.8 2485.85   100.9 2482.80
   111.0 2481.34   171.5 2475.80   191.6 2472.41   201.7 2471.34   211.8 2469.59
   221.9 2467.03   232.0 2463.84   252.2 2456.75   262.2 2452.36   272.3 2446.74
   342.9 2424.13   353.0 2420.34   363.1 2419.94   459.8 2418.72   464.0 2418.69
   474.8 2418.73   494.2 2419.21   544.7 2421.20   595.1 2422.61   736.3 2425.58
   766.6 2426.60   817.0 2427.36   847.3 2428.14   897.7 2428.34   938.0 2429.22
#Mann= 3 , 0 , 0
       0     0.1       0   459.8   0.045       0   474.8     0.1       0
Bank Sta=   459.8,   474.8
Exp/Cntr=0.3,0.1

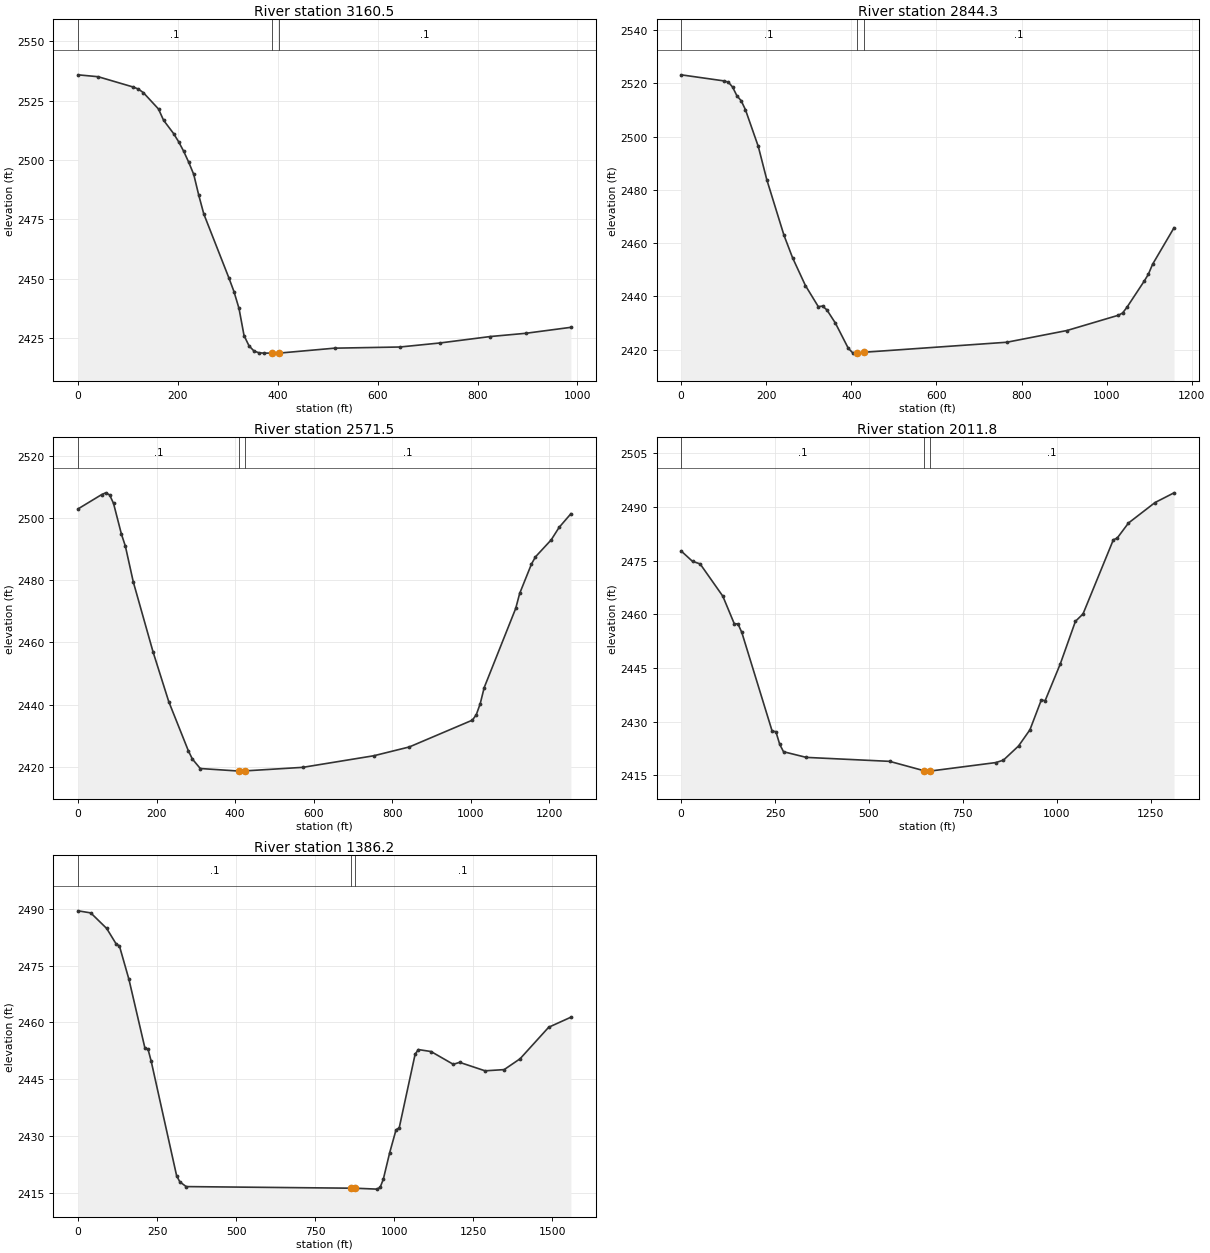
Type RM Length L Ch R = 1 ,3160.5,311.3,316.2,321.3
XS GIS Cut Line= 2
     2055316.045      323161.726     2056253.647      323470.079
#Sta/Elev= 30
       0 2535.89    40.3 2535.09   110.8 2530.73   120.9 2529.88   130.9 2528.36
   161.1 2521.49   171.2 2516.77   191.4 2511.13   201.4 2507.70   211.5 2503.70
   221.6 2499.07   231.6 2493.98   241.7 2485.18   251.8 2477.28   302.1 2450.32
   312.2 2444.60   322.3 2437.49   332.4 2426.05   342.4 2421.72   352.5 2419.52
   362.6 2418.79   372.6 2418.66   388.2 2418.67   403.2 2418.68   513.6 2420.75
   644.6 2421.24   725.2 2422.95   825.9 2425.66   896.4 2427.01   987.0 2429.53
#Mann= 3 , 0 , 0
       0     0.1       0   388.2   0.045       0   403.2     0.1       0
Bank Sta=   388.2,   403.2
Exp/Cntr=0.3,0.1

Type RM Length L Ch R = 1 ,2844.3,273.5,272.8,274.1
XS GIS Cut Line= 2
     2055218.877      323352.591     2056208.298      323954.961
#Sta/Elev= 30
       0 2523.21   100.7 2520.93   110.8 2520.47   120.9 2518.62   131.0 2515.36
   141.0 2513.50   151.1 2510.12   181.3 2496.31   201.4 2483.78   241.8 2462.91
   261.9 2454.51   292.1 2444.09   322.3 2436.18   332.4 2436.37   342.5 2434.95
   362.6 2429.97   392.8 2420.54   402.9 2418.87   413.0 2418.71   414.1 2418.73
   429.1 2419.03   765.5 2422.80   906.5 2427.19  1027.4 2432.92  1037.5 2433.78
  1047.6 2435.88  1087.8 2445.62  1097.9 2448.26  1108.0 2452.07  1158.4 2465.78
#Mann= 3 , 0 , 0
       0     0.1       0   414.1   0.045       0   429.1     0.1       0
Bank Sta=   414.1,   429.1
Exp/Cntr=0.3,0.1

Type RM Length L Ch R = 1 ,2571.5,545,559.7,574.2
XS GIS Cut Line= 2
     2055112.455      323561.635     2056184.067      324214.044
#Sta/Elev= 30
       0 2503.01    60.2 2507.62    70.3 2508.18    80.3 2507.51    90.3 2504.78
   110.4 2494.88   120.4 2491.03   140.5 2479.54   190.7 2457.05   230.8 2440.98
   281.0 2425.05   291.1 2422.46   311.1 2419.42   410.6 2418.59   411.5 2418.58
   425.6 2418.66   572.1 2419.80   752.8 2423.53   843.1 2426.36  1003.7 2434.99
  1013.7 2436.75  1023.7 2440.29  1033.8 2445.47  1114.1 2470.99  1124.1 2475.78
  1154.2 2485.26  1164.3 2487.56  1204.4 2493.04  1224.5 2497.05  1254.6 2501.46
#Mann= 3 , 0 , 0
       0     0.1       0   410.6   0.045       0   425.6     0.1       0
Bank Sta=   410.6,   425.6
Exp/Cntr=0.3,0.1

Type RM Length L Ch R = 1 ,2011.8,623.6,625.6,657.7
XS GIS Cut Line= 2
     2054985.068      323588.399     2055468.388      324808.299
#Sta/Elev= 30
       0 2477.68    30.3 2474.77    50.5 2474.07   111.0 2465.04   141.3 2457.38
   151.4 2457.28   161.5 2454.92   242.2 2427.37   252.3 2427.18   262.4 2423.66
   272.5 2421.59   333.1 2420.01   555.1 2418.90   647.4 2416.26   656.1 2416.17
   662.4 2416.18   837.8 2418.56   858.0 2419.24   898.3 2423.20   928.6 2427.72
   958.9 2436.06   969.0 2435.84  1009.4 2446.12  1049.7 2458.02  1069.9 2460.08
  1150.7 2480.81  1160.8 2481.26  1191.0 2485.49  1261.7 2491.21  1312.2 2493.92
#Mann= 3 , 0 , 0
       0     0.1       0   647.4   0.045       0   662.4     0.1       0
Bank Sta=   647.4,   662.4
Exp/Cntr=0.3,0.1

Type RM Length L Ch R = 1 ,1386.2,1405.3,1386.2,1333.1
XS GIS Cut Line= 2
     2054578.356      323616.640     2054966.611      325127.261
#Sta/Elev= 30
       0 2489.49    40.2 2488.94    90.6 2484.83   120.8 2480.70   130.8 2480.23
   161.0 2471.37   211.3 2453.31   221.4 2452.90   231.4 2449.74   311.9 2419.45
   322.0 2417.85   342.1 2416.58   862.5 2416.16   877.5 2416.15   945.9 2415.91
   956.0 2416.38   966.0 2418.53   986.1 2425.53  1006.3 2431.60  1016.3 2432.11
  1066.6 2451.56  1076.7 2452.81  1117.0 2452.29  1187.4 2448.91  1207.5 2449.43
  1288.0 2447.19  1348.4 2447.51  1398.7 2450.37  1489.3 2458.71  1559.7 2461.37
#Mann= 3 , 0 , 0
       0     0.1       0   862.5   0.045       0   877.5     0.1       0
Bank Sta=   862.5,   877.5
Exp/Cntr=0.3,0.1